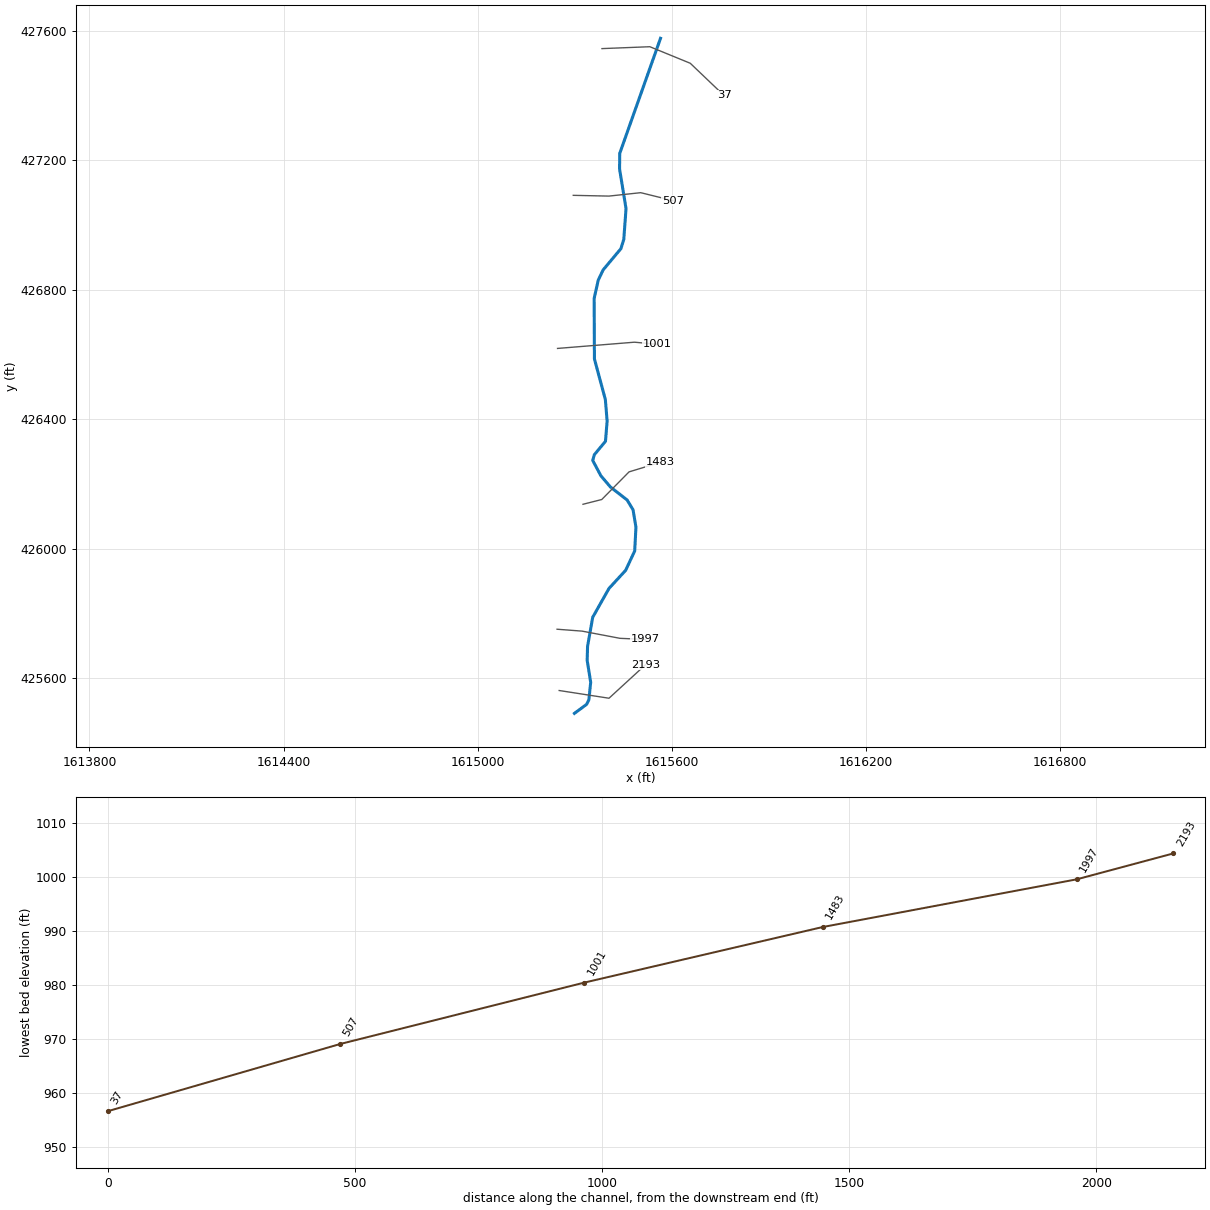
--- MUDRN.prj (project) ---

Proj Title=MUDRN
Current Plan=p01
Default Exp/Contr=0,0
English Units
Geom File=g01
Flow File=f01
Plan File=p01
BEGIN DESCRIPTION:
---------- MODELED AS PART OF WVEMD CTP PROGRAM, 2023----------
Stream Name: Mud Run
Flood Zone:  AFH
Wetzel County, WV
HEC-RAS Version: RAS 6.3
Vertical Datum: NAVD88
Projection: NAD 1983 StatePlane West Virginia S FIPS 4702 (US Feet)
Terrain: 1-meter West Virginia FEMA R3 South Central (collected 2018-2020)
Land Use: 2019 NLCD
Hydrologic Method:
WV SIR2010-5033 regression equations
Additional Model Notes:
None
END DESCRIPTION:
DSS Export Rating Curves= 0
DSS Export Rating Curve Sorted= 0
DSS Export Volume Flow Curves= 0
DXF OffsetX= 0
DXF OffsetY= 0
DXF ScaleX= 0
DXF ScaleY= 0

--- MUDRN.p01 (plan) ---

Plan Title=Floodplain
Program Version=6.30
Short Identifier=Floodplain
Geom File=g01
Flow File=f01
Subcritical Flow
K Sum by GR= 0
Std Step Tol= 0.01
Critical Tol= 0.01
Num of Std Step Trials= 20
Max Error Tol= 0.3
Flow Tol Ratio= 0.001
Split Flow NTrial= 30
Split Flow Tol= 0.02
Split Flow Ratio= 0.02
Log Output Level= 0
Friction Slope Method= 1
Unsteady Friction Slope Method= 2
Unsteady Bridges Friction Slope Method= 1
Parabolic Critical Depth
Global Vel Dist= 0 , 0 , 0
Global Log Level= 0
CheckData=True
Encroach Param=-1 ,0,0, 0
Mapping Interval=1HOUR
Computation Time Step Use Courant=        0
Computation Time Step Use Time Series=    0
Computation Time Step Count To Double=0
Computation Time Step Max Doubling=0
Computation Time Step Max Halving=0
Computation Time Step Residence Courant=0
Run HTab= 0
Run UNet= 0
Run Sediment= 0
Run PostProcess= 0
Run WQNet= 0
Run RASMapper=-1
UNET Theta= 0
UNET Theta Warmup= 0
UNET ZTol= 0
UNET ZSATol= 0
UNET MxIter= 0
UNET Max Iter WO Improvement= 0
UNET MaxInSteps= 0
UNET DtIC= 0
UNET DtMin= 0
UNET MaxCRTS= 0
UNET WFStab= 0
UNET SFStab= 0
UNET WFX= 1
UNET SFX= 1
UNET Gravity=32.17405
UNET 1D Methodology=Finite Difference
UNET DSS MLevel= 1
UNET Pardiso=0
UNET DZMax Abort= 0
UNET Use Existing IB Tables= 0
UNET Froude Reduction=False
UNET Froude Limit= 0
UNET Froude Power= 0
UNET D1 Cores= 0
UNET WindReference=Eulerian
UNET WindDragFormulation=Hsu (1988)
UNET D2 Coriolis=0
UNET D2 Cores= 0
UNET D2 Theta= 1
UNET D2 Theta Warmup= 1
UNET D2 Z Tol= 0.01
UNET D2 Volume Tol= 0.01
UNET D2 Max Iterations= 20
UNET D2 Equation= 0
UNET D2 RampUpFraction=0.1
UNET D2 TimeSlices= 1
UNET D2 Turbulence Formulation=Non-Conservative (original)
UNET D2 Eddy Viscosity=0.3
UNET D2 Transverse Eddy Viscosity=0.1
UNET D2 Smagorinsky Mixing=0
UNET D2 BCVolumeCheck=0
UNET D2 Cores=0
UNET D2 SolverType=PARDISO (Direct)
UNET D2 Minimum Iterations= 3
UNET D2 Maximum Iterations= 30
UNET D2 Restart Number= 10
UNET D2 Relaxation Coeff=1.3
UNET D2 SOR Precondition Iterations= 10
UNET D2 ILUT Maximum Fill= 8
UNET D2 ILUT Tolerance=1E-08
UNET D2 Convergence Tolerance=0.00001
UNET D1D2 MaxIter= 0
UNET D1D2 ZTol=0.01
UNET D1D2 QTol=0.1
UNET D1D2 MinQTol=1
Write IC File= 0
Write IC File at Fixed DateTime=0
Write IC File at Sim End=0
Echo Input=False
Echo Parameters=False
Echo Output=False
Write Detailed= 0
HDF Write Warmup=0
HDF Write Time Slices=0
HDF Flush=0
HDF Compression= 1
HDF Chunk Size= 1
HDF Spatial Parts= 1
HDF Use Max Rows=0
HDF Fixed Rows= 1
Calibration Method= 0
Calibration Iterations= 20
Calibration Max Change=0.05
Calibration Tolerance=0.2
Calibration Maximum=1.5
Calibration Minimum=0.5
Calibration Optimization Method= 1
WQ AD Non Conservative
WQ ULTIMATE=-1
WQ Max Comp Step=1HOUR
WQ Output Interval=15MIN
WQ Output Selected Increments= 0
WQ Output face flow=0
WQ Output face velocity=0
WQ Output face area=0
WQ Output face dispersion=0
WQ Output cell volume=0
WQ Output cell surface area=0
WQ Output cell continuity=0
WQ Output cumulative cell continuity=0
WQ Output face conc=0
WQ Output face dconc_dx=0
WQ Output face courant=0
WQ Output face peclet=0
WQ Output face adv mass=0
WQ Output face disp mass=0
WQ Output cell mass=0
WQ Output cell source sink temp=0
WQ Output nsm pathways=0
WQ Output nsm derived pathways=0
WQ Create Restart=0
WQ Fixed Restart=0
WQ System Summary=0
WQ Write To DSS=0
Sorting and Armoring Iterations= 10
XS Update Threshold= 0.02
Bed Roughness Predictor= 0
Hydraulics Update Threshold= 0.02
Energy Slope Method= 1
Volume Change Method= 1
Sediment Retention Method= 0
Sediment TS Multiplier= 1
Warm Up Method= 0
XS Weighting Method= 0
Number of US Weighted Cross Sections= 1
Number of DS Weighted Cross Sections= 1
Upstream XS Weight=0
Main XS Weight=1
Downstream XS Weight=0
Number of DS XS's Weighted with US Boundary= 1
Upstream Boundary Weight= 1
Weight of XSs Associated with US Boundary= 0
Number of US XS's Weighted with DS Boundary= 1
Downstream Boundary Weight= 0.5
Weight of XSs Associated with DS Boundary= 0.5
Percentile Method= 0
Sediment Output Level= 3
Mass or Volume Output= 0
Output Increment Type= 1
Profile and TS Output Increment= 1
Transport Output Increment 1
XS Output Flag= 0
XS Output Increment= 10
Read HDF5 Sediment Hotstart= 0
Sediment Hotstart Type= 0
Write Gradation File= 0
Read Gradation Hotstart= 0
Write HDF5 File= 1
Write Binary Output= 1
Write DSS Sediment File= 0
DSS Sediment Output Type= 1
SV Curve= 0
Specific Gage Flag= 0
Subcell Erosion Methods= 0
Subcell Deposition Methods= 0
Advection Scheme= 1
Matrix Solver= 0
Implicit Weighting Factor= 1
Maximum Outer Loop Convergence Iterations= 5
Convergence Maximum Absolute= 0.001
Convergence RMSE= 0.0001
Grain Fractions Max Abs Error= 0.001
Max Subgrid Regions= 1
Max Subgrid Length Scale= 3.402823E+38
Initial Layer Thickness= 3.402823E+38
Min Layer Thickness= 3.402823E+38
Max Layer Thickness= 3.402823E+38
Number of Layers= 5

--- MUDRN.f01 (steady flow) ---

Flow Title=Flow
Program Version=6.30
Number of Profiles= 1
Profile Names=F01pct
River Rch & RM=MUDRN,Main,2193
     651
Boundary for River Rch & Prof#=MUDRN,Main            , 1
Up Type= 0
Dn Type= 3
Dn Slope=0.02636
DSS Import GetInterval= 0
DSS Import GetPeak= 0
DSS Import FillOption= 0

--- MUDRN.g01 (geometry) ---

Geom Title=Geometry
Program Version=6.30

River Reach=MUDRN           ,Main
Reach XY= 30
1615298.77701073425490.788790783 1615336.2900118425518.626242242
 1615343.4141969425532.879141516     1615348.985      425586.893
     1615338.082      425654.874     1615339.354      425698.129
     1615355.257      425787.819     1615405.508      425876.872
     1615457.032      425932.849      1615485.02      425992.642
     1615488.837      426066.429     1615479.932      426119.861
     1615461.485      426150.394     1615409.961      426190.468
     1615380.701      426224.817     1615355.257      426272.524
     1615360.346      426290.335     1615394.695      426331.681
     1615399.784      426394.019     1615394.313      426460.758
     1615360.523      426586.145     1615359.709      426773.412
     1615372.329      426829.592     1615387.392      426861.346
     1615442.351       426926.89     1615451.307      426955.794
     1615458.228      427050.648      1615438.28      427173.186
     1615438.687      427221.224     1615564.785      427577.029

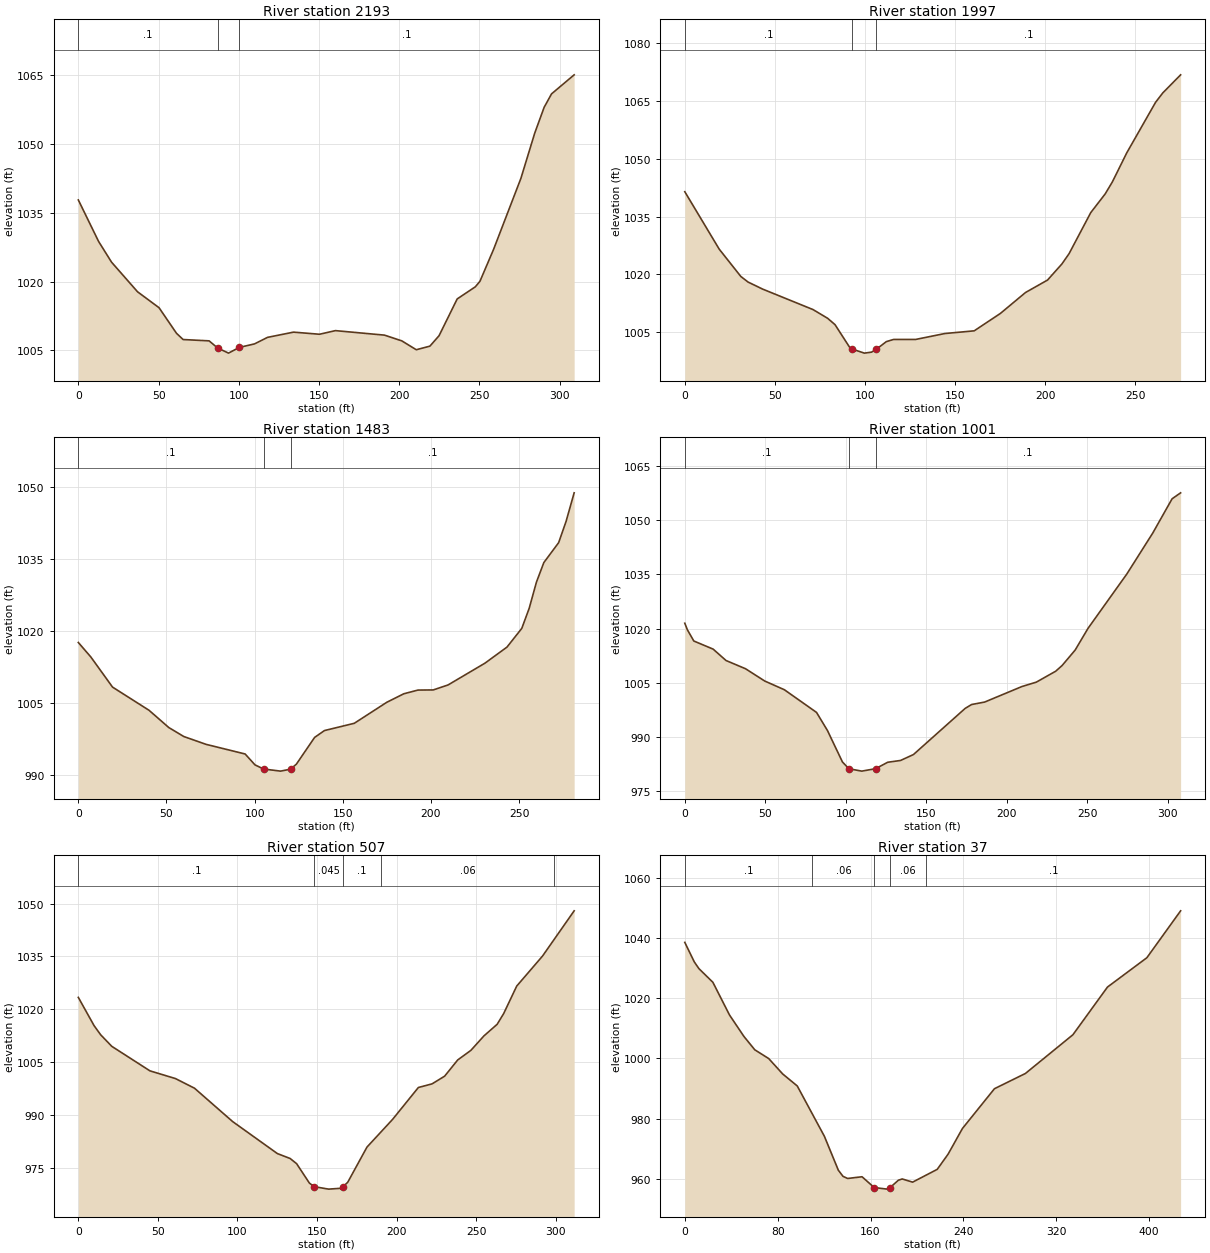
Type RM Length L Ch R = 1 ,2193    ,195.2,195.6,194.8
XS GIS Cut Line= 3
1615251.61574514425561.4680543741615405.56117532425537.586503018
1615518.44150304425641.124054915
#Sta/Elev= 30
       0 1037.78    12.6 1028.76    20.7 1024.23    36.9 1017.78    50.3 1014.31
    61.2 1008.73    65.3 1007.38    81.5 1007.09   86.791005.549    93.6 1004.42
  100.211005.654   109.8 1006.43   117.9 1007.85   134.1 1008.99   150.3 1008.53
   160.2 1009.32   190.8 1008.34   201.6 1007.09   210.6 1005.16   219.1 1005.94
   224.8 1008.21   236.1 1016.22   247.4 1018.86   250.3 1020.07   258.8 1027.03
   275.8 1042.47   284.4  1052.3   290.3 1057.96   294.9 1060.88     309 1065.03
#Mann= 3 ,-1,0
       0      .1       0   86.79    .045       0  100.21      .1       0
Bank Sta=86.79,100.21
XS Rating Curve= 0 ,0
Exp/Cntr(USF)=0,0
Exp/Cntr=0.3,0.1

Type RM Length L Ch R = 1 ,1997    ,511.9,514.1,526.4
XS GIS Cut Line= 4
1615245.07058616425750.8526167231615322.37168993425744.996472498
1615439.49457443425722.7431244441615517.96690704425719.229437909
#Sta/Elev= 30
       0 1041.45    19.1 1026.57    31.1 1019.49    35.1 1018.04    43.2 1016.21
    71.2  1010.9    79.3 1008.64    83.4    1007    91.5 1001.14    93.1 1000.64
    99.7  999.61   103.7  999.87  106.431000.636   111.9 1002.59   115.9 1003.15
   128.2 1003.16   144.4 1004.69   160.7 1005.39   175.2 1009.89   189.2 1015.33
   201.4 1018.55   209.4 1022.73   213.4 1025.42   225.4 1036.03   233.4 1040.87
   237.4 1043.99   245.4 1051.53   261.4 1064.63   265.4 1067.06   275.3 1071.75
#Mann= 3 ,-1,0
       0      .1       0    93.1    .045       0  106.43      .1       0
Bank Sta=93.1,106.43
XS Rating Curve= 0 ,0
Exp/Cntr(USF)=0,0
Exp/Cntr=0.3,0.1

Type RM Length L Ch R = 1 ,1483    ,482.1,482,470.8
XS GIS Cut Line= 4
1615325.26752246426137.0280993011615383.24335028426151.785582748
1615467.57182712426237.1681655451615564.54957548426266.683132438
#Sta/Elev= 30
       0 1017.54     7.1 1014.52    19.4 1008.25    40.1 1003.42    51.3  999.83
    59.8  997.96    72.4  996.33    94.6  994.32   100.2  992.05  105.06991.1908
   114.7  990.75   120.4  991.16   123.7  992.22     134  997.77   139.6   999.2
   156.5 1000.71   174.9 1005.08   184.6 1006.86   192.6 1007.63   201.3 1007.66
   209.7  1008.7   230.6 1013.23   243.1 1016.58   251.5 1020.48   255.7 1024.66
   259.8  1030.1     264 1034.18   272.4 1038.33   276.6 1042.74   281.2 1048.71
#Mann= 3 ,-1,0
       0      .1       0  105.06    .045       0   120.4      .1       0
Bank Sta=105.06,120.4
XS Rating Curve= 0 ,0
Exp/Cntr(USF)=0,0
Exp/Cntr=0.3,0.1

Type RM Length L Ch R = 1 ,1001    ,494.5,494.3,495.7
XS GIS Cut Line= 3
1615246.55072907426618.6837780781615484.33107071426637.963265238
 1615553.4158997426631.536769518
#Sta/Elev= 30
       0 1021.48     1.6 1019.66     5.6 1016.54    17.6 1014.29    25.6 1011.13
    37.7 1008.85    49.7 1005.42    61.8 1003.03    81.8  996.73    88.6   991.7
    97.9  982.98   101.9   981.1   109.9  980.44  118.52981.1208     126   982.9
     134   983.4     142  985.04   174.1  997.84   178.1  998.92   186.2   999.6
   209.3  1003.9   218.3 1005.13   230.3 1008.15   234.3 1009.74   242.4 1014.02
   250.4 1020.05   274.5 1035.13   290.6 1046.49   302.6 1055.99   307.9 1057.65
#Mann= 3 ,-1,0
       0      .1       0   101.9    .045       0  118.52      .1       0
Bank Sta=101.9,118.52
XS Rating Curve= 0 ,0
Exp/Cntr(USF)=0,0
Exp/Cntr=0.3,0.1

Type RM Length L Ch R = 1 ,507     ,474.3,470.4,466
XS GIS Cut Line= 4
1615295.13083757427091.819901449  1615405.226349 427089.47744376
1615503.60957198427100.018503364 1615603.1640238 427075.42269762
#Sta/Elev= 30
       0  1023.4     9.9 1015.39      14 1012.82      21 1009.53      45 1002.57
      61 1000.39      73  997.65      97  988.18   125.1  979.11   133.1  977.72
   137.2  976.24   145.2  970.75  148.22969.7308   157.3  969.03   165.3  969.28
   166.4  969.75   169.3  970.97   181.4  980.95   197.5  988.81   213.7  997.85
   222.3  998.88   230.2 1001.06   238.4 1005.65   246.7 1008.38   254.9 1012.48
   263.2 1015.77   267.3 1018.81   275.5 1026.61   291.7 1035.11   311.6 1047.95
#Mann= 5 ,-1,0
       0      .1       0  148.22    .045       0   166.4      .1       0
  190.12     .06       0  299.07      .1       0
Bank Sta=148.22,166.4
XS Rating Curve= 0 ,0
Exp/Cntr(USF)=0,0
Exp/Cntr=0.3,0.1

Type RM Length L Ch R = 1 ,37      ,,,
XS GIS Cut Line= 4
 1615383.8884019427545.2768644341615531.82986853427551.122003248
1615656.69822453427500.0145245941615761.05471461 427400.40151133
#Sta/Elev= 30
       0 1038.53     8.2 1032.03    12.2 1029.79    24.2 1025.27    38.5 1014.42
      51 1007.25    60.3 1002.84    72.3  999.93    84.3  994.83    96.9  990.82
   120.3  974.08   132.3  962.83   136.3   960.8   140.3  960.09   152.7  960.66
163.2186957.0777   174.3  956.55176.9172957.0828     184   959.5   187.3  959.93
   196.3  958.87   217.5  963.12   226.9  968.19   239.2  976.69   266.8  989.91
   293.5  994.98   334.4 1007.84   364.2 1023.69   398.1 1033.42   427.2 1049.01
#Mann= 5 ,-1,0
       0      .1       0     110     .06       0163.2186    .045       0
176.9172     .06       0  208.06      .1       0
Bank Sta=163.2186,176.9172
XS Rating Curve= 0 ,0
Exp/Cntr(USF)=0,0
Exp/Cntr=0.3,0.1
LCMann Table=0

Chan Stop Cuts=-1
Use User Specified Reach Order=0
Composite Channel Slope=5